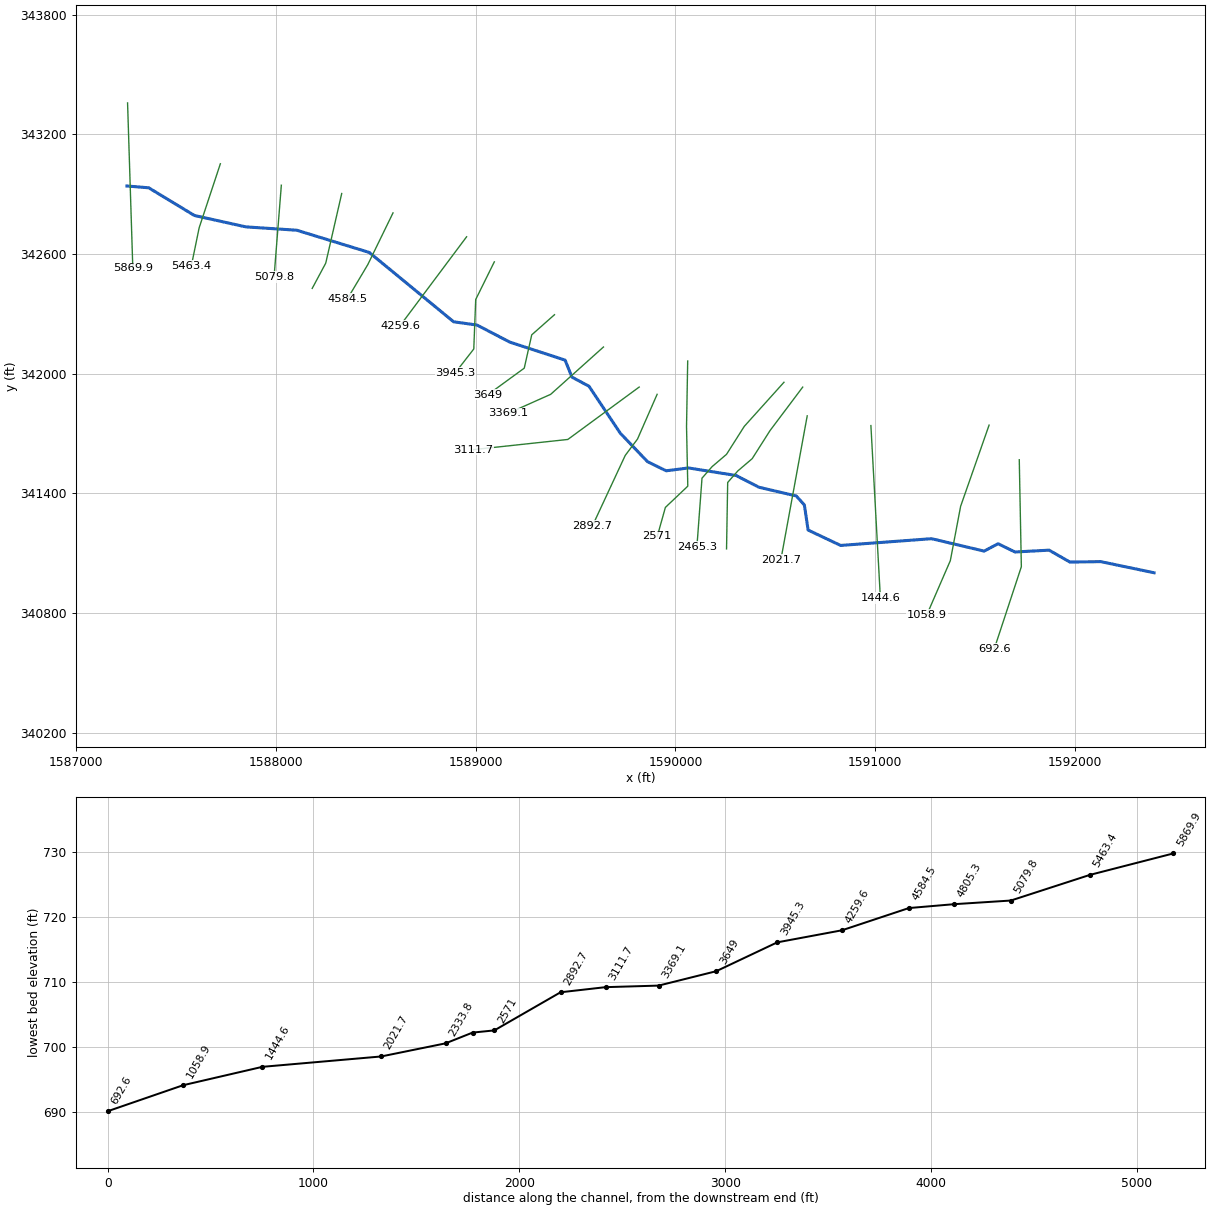
--- WHLRRN.prj (project) ---

Proj Title=WHLRRN
Current Plan=p01
Default Exp/Contr=0,0
English Units
Geom File=g01
Flow File=f01
Plan File=p01
BEGIN DESCRIPTION:
END DESCRIPTION:
DSS Export Rating Curves= 0
DSS Export Rating Curve Sorted= 0
DSS Export Volume Flow Curves= 0
DXF OffsetX= 0
DXF OffsetY= 0
DXF ScaleX= 0
DXF ScaleY= 0

--- WHLRRN.p01 (plan) ---

Plan Title=Floodplain
Program Version=4.00
Geom File=g01
Flow File=f01
K Sum by GR=0
Std Step Tol=0.01
Critical Tol=0.01
Num of Std Step Trials=20
Max Error Tol=0.3
Flow Tol Ratio=0.001
Split Flow NTrial=30
Split Flow Tol=0.02
Split Flow Ratio=0.02
Log Output Level=0
Friction Slope Method=1
Unsteady Friction Slope Method=2
Unsteady Bridges Friction Slope Method=1
Global Log Level=0
CheckData=False
Run HTab=0
Run UNet=0
Run PostProcess=0
UNET Theta=0
UNET Theta Warmup=0
UNET ZTol=0
UNET ZSATol=0
UNET MxIter=0
UNET MaxInSteps=0
UNET DtIC=0
UNET DtMin=0
UNET MaxCRTS=0
UNET WFStab=0
UNET SFStab=0
UNET WFX=0
UNET SFX=0
UNET DSS MLevel=0
UNET DZMax Abort=0
UNET Convert EG Bridges=0
UNET Use Existing IB Tables=0
UNET Froude Limit=0
UNET Froude Power=0
Write IC File=0
Echo Input=False
Echo Output=False
Write Detailed=0

--- WHLRRN.f01 (steady flow) ---

Flow Title=NFF Regression Equation
Program Version=4.10
Number of Profiles= 1
Profile Names=P100yr
River Rch & RM=WHLRRN,Main            ,5869.9
     894
River Rch & RM=WHLRRN,Main            ,4584.5
     911
River Rch & RM=WHLRRN,Main            ,2333.8
    1100
River Rch & RM=WHLRRN,Main            ,2021.7
    1114
River Rch & RM=WHLRRN,Main            ,692.6
    1158
Boundary for River Rch & Prof#=WHLRRN,Main            , 1
Up Type= 0
Dn Type= 3
Dn Slope=0.01
DSS Import GetInterval= 0
DSS Import GetPeak= 0
DSS Import FillOption= 0

--- WHLRRN.g01 (geometry) ---

Geom Title=USGS 10m DEM
Program Version=4.10

River Reach=WHLRRN          ,Main
Reach XY= 30
      1587255.73       342941.61     1587364.371      342932.506
     1587592.768      342793.807     1587850.754      342736.516
     1588104.921      342719.849     1588467.768      342608.391
     1588889.816      342260.735     1589007.004      342244.241
     1589171.059      342158.815     1589447.751      342068.385
      1589481.83      341983.391     1589567.266      341937.434
     1589723.959      341701.809     1589860.112      341559.265
     1589953.126      341513.615     1590064.845      341527.817
     1590303.126      341490.004     1590417.709      341430.976
     1590604.402      341387.396     1590644.881      341341.937
     1590663.542      341216.393     1590826.275      341139.294
     1591281.483      341173.148      1591544.12      341110.895
      1591614.12      341147.784     1591698.697      341106.498
     1591869.443      341115.626     1591973.625      341055.831
     1592127.232       341058.17     1592394.506       341002.32

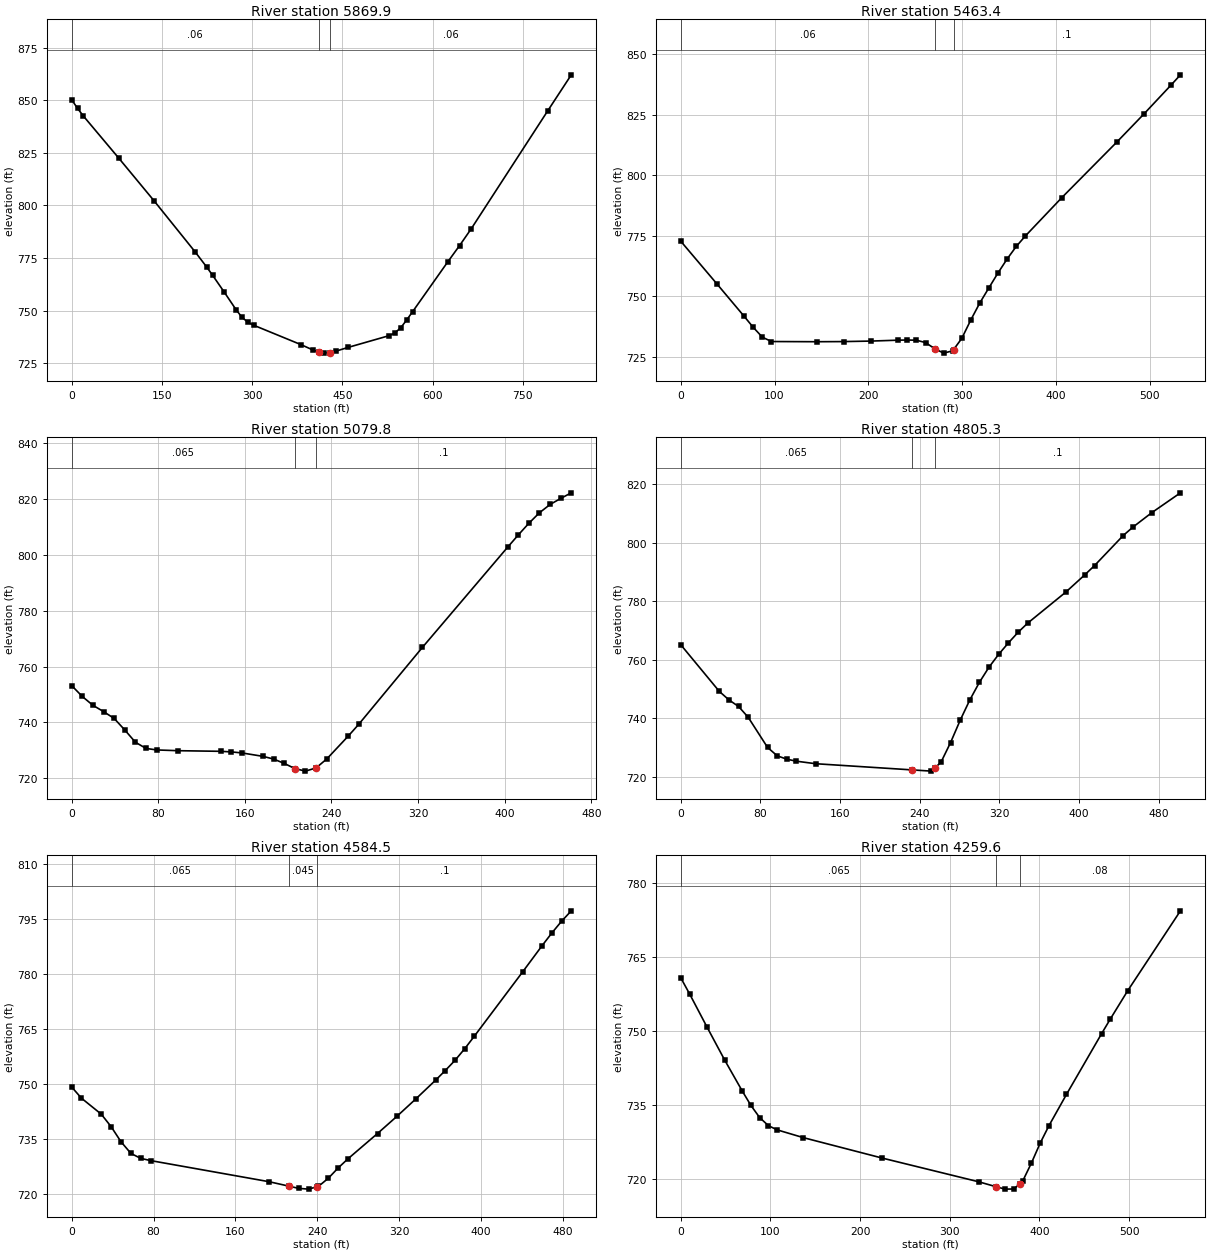
Type RM Length L Ch R = 1 ,5869.9  ,414,406.5,398
XS GIS Cut Line= 2
     1587258.483      343358.122     1587284.775      342528.156
#Sta/Elev= 30
       0  850.24     9.8  846.11    19.5  842.47    78.2   822.5   136.8  802.26
   205.2  777.95   224.7  770.64   234.5  766.73     254  758.66   273.5  750.38
   283.3   746.8   293.1  744.45   302.8  743.06     381  733.89   400.5   731.4
   410.3   730.3   420.1  729.84   429.8  730.08   439.6  730.81   459.2  732.54
   527.5  738.13   537.3  739.44   547.1  741.95   556.8  745.58   566.6   749.5
   625.2  773.23   644.8  780.96   664.3  788.99   791.3  844.96   830.4  862.04
#Mann= 3 , 0 , 0
       0     .06       0   410.3    .045       0   429.8     .06       0
Bank Sta=410.3,429.8
XS Rating Curve= 0 ,0
Exp/Cntr=0.3,0.1

Type RM Length L Ch R = 1 ,5463.4  ,377.8,383.6,388.7
XS GIS Cut Line= 3
     1587722.747       343053.03     1587616.617      342731.774
     1587577.535      342541.195
#Sta/Elev= 30
       0  772.72    38.7  755.03    67.7  741.66    77.3  737.15      87  733.11
    96.7  731.31     145  731.23     174  731.29     203   731.5     232  731.87
   241.7  731.93   251.3  731.85     261  730.88   270.7  728.39   280.3  726.52
     290  727.48     291  728.01   299.7  732.61   309.3  740.21     319   747.3
   328.7  753.54   338.3  759.63   348.1  765.43   357.8  770.58   367.5   774.9
   406.4  790.74   464.8  813.58     494   825.3   523.2  837.35   532.9  841.45
#Mann= 3 , 0 , 0
       0     .06       0   270.7    .045       0     291      .1       0
Bank Sta=270.7,291
XS Rating Curve= 0 ,0
Exp/Cntr=0.3,0.1

Type RM Length L Ch R = 1 ,5079.8  ,277.5,274.5,270.9
XS GIS Cut Line= 2
     1588027.876      342945.567     1587991.418      342485.497
#Sta/Elev= 30
       0  753.23     9.8  749.33    19.6  746.17    29.5  743.89    39.3  741.44
    49.1   737.3    58.9  732.92    68.7   730.7    78.6  730.16    98.2  729.89
   137.5  729.67   147.3  729.46   157.1   729.1   176.8  727.86   186.6  726.89
   196.4  725.33   206.2  723.48     216  722.57   225.8  723.73   235.7  726.95
   255.3  735.05   265.1  739.31     324  766.91   402.6  802.75   412.4  807.13
   422.2  811.32     432  815.11   441.9   818.1   451.7  820.27   461.5  822.28
#Mann= 3 , 0 , 0
       0    .065       0   206.2    .045       0   225.8      .1       0
Bank Sta=206.2,225.8
XS Rating Curve= 0 ,0
Exp/Cntr=0.3,0.1

Type RM Length L Ch R = 1 ,4805.3  ,225.9,220.8,215.6
XS GIS Cut Line= 3
     1588329.959        342903.9     1588250.098      342554.942
      1588182.39      342428.205
#Sta/Elev= 30
       0  765.14    38.7  749.22    48.4  746.31      58  744.08    67.7  740.38
    87.1  730.11    96.8  727.24   106.4  726.09   116.1   725.4   135.4  724.54
   232.2  722.43   251.6  722.01   255.4   723.2   261.2  725.01   270.9  731.77
   280.6  739.42   290.2   746.3   299.9  752.36   309.6  757.56   319.3  761.92
     329   765.8   338.6  769.37   348.3  772.52   386.7  783.15   405.9  789.09
   415.5  792.19   444.2  802.42   453.8  805.25   472.9  810.23   501.7  817.01
#Mann= 3 , 0 , 0
       0    .065       0   232.2    .045       0   255.4      .1       0
Bank Sta=232.2,255.4
XS Rating Curve= 0 ,0
Exp/Cntr=0.3,0.1

Type RM Length L Ch R = 1 ,4584.5  ,329,325,320.4
XS GIS Cut Line= 3
     1588586.728      342806.856     1588460.112      342546.752
     1588358.437      342375.878
#Sta/Elev= 30
       0  749.21     9.6  746.16    28.9  741.82    38.6   738.4    48.2  734.31
    57.9  731.13    67.5  729.78    77.1  729.18   192.9  723.43   212.1  722.23
   221.8  721.62   231.4  721.41   239.9  722.07   241.1  722.16   250.7  724.36
   260.4  727.19     270  729.68   298.8  736.55   317.7  741.21   336.6  746.06
   355.6  751.08     365  753.69   374.5  756.46     384  759.63   393.4  763.04
   440.8  780.62   459.7  787.72   469.2  791.16   478.6  794.32   488.1  797.16
#Mann= 3 , 0 , 0
       0    .065       0   212.1    .045       0   239.9      .1       0
Bank Sta=212.1,239.9
XS Rating Curve= 0 ,0
Exp/Cntr=0.3,0.1

Type RM Length L Ch R = 1 ,4259.6  ,300.4,314.3,327.7
XS GIS Cut Line= 2
     1588954.948      342687.043     1588621.638      342240.548
#Sta/Elev= 25
       0  760.76     9.8  757.52    29.3  750.78    48.9  744.13    68.4  737.89
    78.2  734.93      88  732.46    97.8  730.82   107.5  729.98   136.8   728.4
   224.8  724.26   332.4  719.46   351.9  718.45   361.7  717.98   371.5  718.01
   378.2  719.09   381.2  719.58     391  723.26   400.8   727.3   410.6  730.84
   430.1  737.16   469.2  749.44     479  752.43   498.5  758.19   557.2  774.34
#Mann= 3 , 0 , 0
       0    .065       0   351.9    .045       0   378.2     .08       0
Bank Sta=351.9,378.2
XS Rating Curve= 0 ,0
Exp/Cntr=0.3,0.1

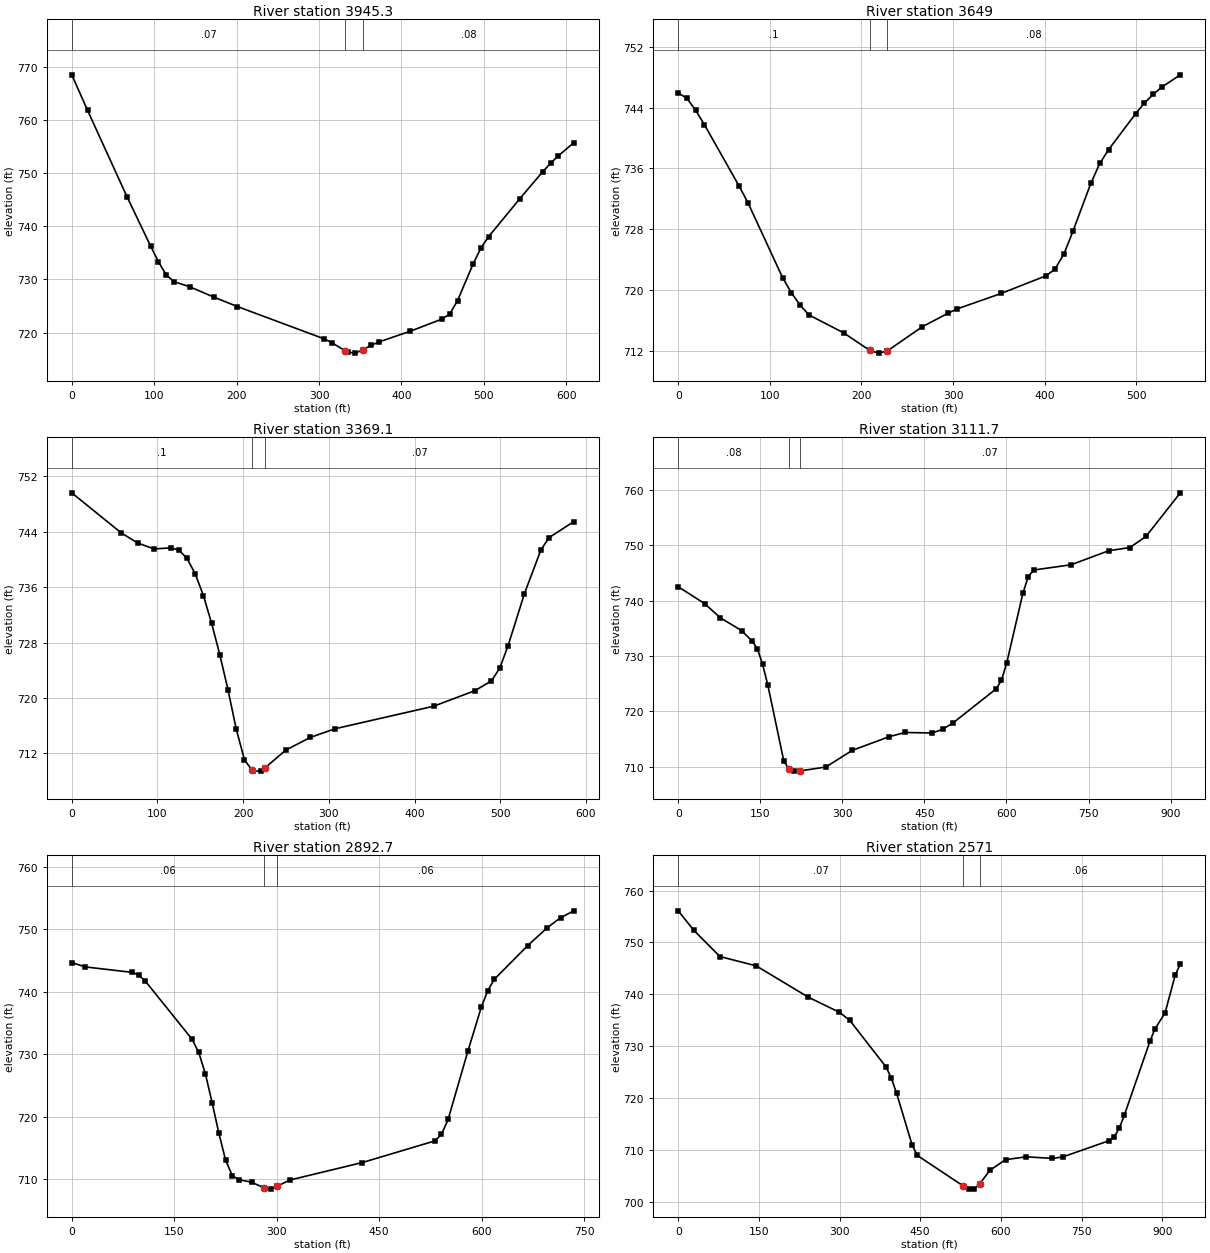
Type RM Length L Ch R = 1 ,3945.3  ,300.4,296.3,291.7
XS GIS Cut Line= 4
     1589093.467      342561.205     1589000.415      342372.509
     1588990.748      342124.385     1588898.564      342005.453
#Sta/Elev= 30
       0  768.53    19.1  761.86    66.9  745.61    95.6   736.3   105.2  733.31
   114.8  730.81   124.3  729.57   143.4   728.6   172.1  726.69   200.8   724.9
   305.9  718.83   315.4  718.11   331.7  716.56   334.6   716.3   344.1  716.12
   353.6  716.78   363.2  717.59   372.8  718.23     411  720.26   449.2  722.54
   458.7  723.51   468.1  726.02   486.9  732.89   496.3  735.88   505.7  738.04
   543.4  745.16   571.6  750.32     581  751.88   590.4  753.28   609.2  755.75
#Mann= 3 , 0 , 0
       0     .07       0   331.7    .045       0   353.6     .08       0
Bank Sta=331.7,353.6
XS Rating Curve= 0 ,0
Exp/Cntr=0.3,0.1

Type RM Length L Ch R = 1 ,3649    ,293.6,279.9,265.5
XS GIS Cut Line= 4
     1589394.546      342296.142     1589280.729      342195.292
      1589243.27      342028.168     1589061.739      341895.621
#Sta/Elev= 30
       0  745.96     9.5  745.24      19  743.66    28.5  741.79    66.5  733.67
      76  731.51     114   721.6   123.6  719.61   133.1  717.99   142.6  716.71
   180.6  714.34   209.2  712.02   218.7  711.67   228.2  711.95   266.2  715.13
   294.8  716.94   304.3  717.49   352.7  719.54   401.5  721.86   411.3  722.74
   421.1  724.75   430.8   727.7   450.4  734.04   460.2  736.66   469.9   738.5
   499.2   743.2     509  744.64   518.8  745.81   528.6  746.78   548.1  748.34
#Mann= 3 , 0 , 0
       0      .1       0   209.2    .045       0   228.2     .08       0
Bank Sta=209.2,228.2
XS Rating Curve= 0 ,0
Exp/Cntr=0.3,0.1

Type RM Length L Ch R = 1 ,3369.1  ,259.4,257.5,255.1
XS GIS Cut Line= 3
     1589639.545      342134.238     1589375.444      341896.902
     1589164.797      341802.737
#Sta/Elev= 30
       0   749.6    57.6  743.83    76.8  742.37      96   741.5   115.2  741.66
   124.8  741.37   134.4  740.15     144  737.92   153.6  734.78   163.1  730.81
   172.7  726.26   182.3  721.18   191.9  715.51   201.5  711.09   210.2   709.6
   211.1  709.45   220.7  709.46   225.2  709.89   249.5  712.47   278.3  714.31
   307.1  715.56   422.4  718.82   470.4  721.06   489.7  722.47   499.3  724.31
   508.9  727.48   528.1  735.04   547.4  741.38     557  743.15   585.8  745.45
#Mann= 3 , 0 , 0
       0      .1       0   210.2    .045       0   225.2     .07       0
Bank Sta=210.2,225.2
XS Rating Curve= 0 ,0
Exp/Cntr=0.3,0.1

Type RM Length L Ch R = 1 ,3111.7  ,212.2,218.9,225.5
XS GIS Cut Line= 5
     1589818.327      341933.414     1589461.156      341670.608
     1589460.556      341670.632     1588993.512      341620.219
     1588989.682      341619.178
#Sta/Elev= 30
       0  742.52    48.2  739.48    77.1   736.9   115.7  734.61     135  732.71
   144.6  731.32   154.2  728.52   163.9   724.7   192.8  711.11   202.4  709.53
   212.1  709.21   221.7  709.23   269.9  709.96   318.1  712.96   385.6  715.43
   414.5  716.19   463.6   716.1   483.2  716.75   502.8  717.96     581  724.06
   590.8  725.59   600.6   728.8     630  741.33   639.8  744.34   649.6  745.54
   718.1  746.49   786.6  749.02   825.7  749.61   855.1  751.62   917.8  759.49
#Mann= 3 , 0 , 0
       0     .08       0   202.4    .045       0   221.7     .07       0
Bank Sta=202.4,221.7
XS Rating Curve= 0 ,0
Exp/Cntr=0.3,0.1

Type RM Length L Ch R = 1 ,2892.7  ,306.5,321.7,336.6
XS GIS Cut Line= 4
     1589908.084      341896.955     1589809.973      341672.835
     1589748.487      341590.565     1589585.168      341238.969
#Sta/Elev= 30
       0  744.67    19.6  743.97    88.1   743.1    97.9  742.68   107.6  741.71
   176.2  732.38   185.9  730.28   195.7  726.83   205.5  722.22   215.3  717.38
   225.1  713.09   234.9  710.59   244.6  709.93   263.3  709.53     282  708.59
   291.3  708.42   300.7   708.9   319.4  709.88   424.9  712.66   531.5  716.13
   541.2  717.16   550.9  719.56     580  730.53   599.4  737.49     609  740.19
   618.7     742   667.2  747.35   696.3  750.26   715.6  751.84     735  752.94
#Mann= 3 , 0 , 0
       0     .06       0     282    .045       0   300.7     .06       0
Bank Sta=282,300.7
XS Rating Curve= 0 ,0
Exp/Cntr=0.3,0.1

Type RM Length L Ch R = 1 ,2571    ,123.7,105.8,86.6
XS GIS Cut Line= 5
     1590061.054       342064.18     1590055.232      341735.447
     1590061.535      341436.406     1589949.401      341329.896
     1589908.698      341184.407
#Sta/Elev= 30
       0  756.09      29  752.34    77.4   747.3     145   745.5   241.8  739.48
   299.8  736.56   319.1     735   386.7  726.01   396.3  723.85     406  721.01
   434.9  711.03   444.6  709.02   529.1  703.21     541  702.54   550.7  702.59
   560.4  703.54   579.6  706.16   608.6  708.21   647.2  708.76   695.6  708.45
   714.9  708.73   801.4  711.87   810.9  712.62   820.3  714.31   829.8  716.85
     877  730.95   886.4  733.36   905.3  736.46   924.2  743.75   933.6  745.86
#Mann= 3 , 0 , 0
       0     .07       0   529.1    .045       0   560.4     .06       0
Bank Sta=529.1,560.4
XS Rating Curve= 0 ,0
Exp/Cntr=0.3,0.1

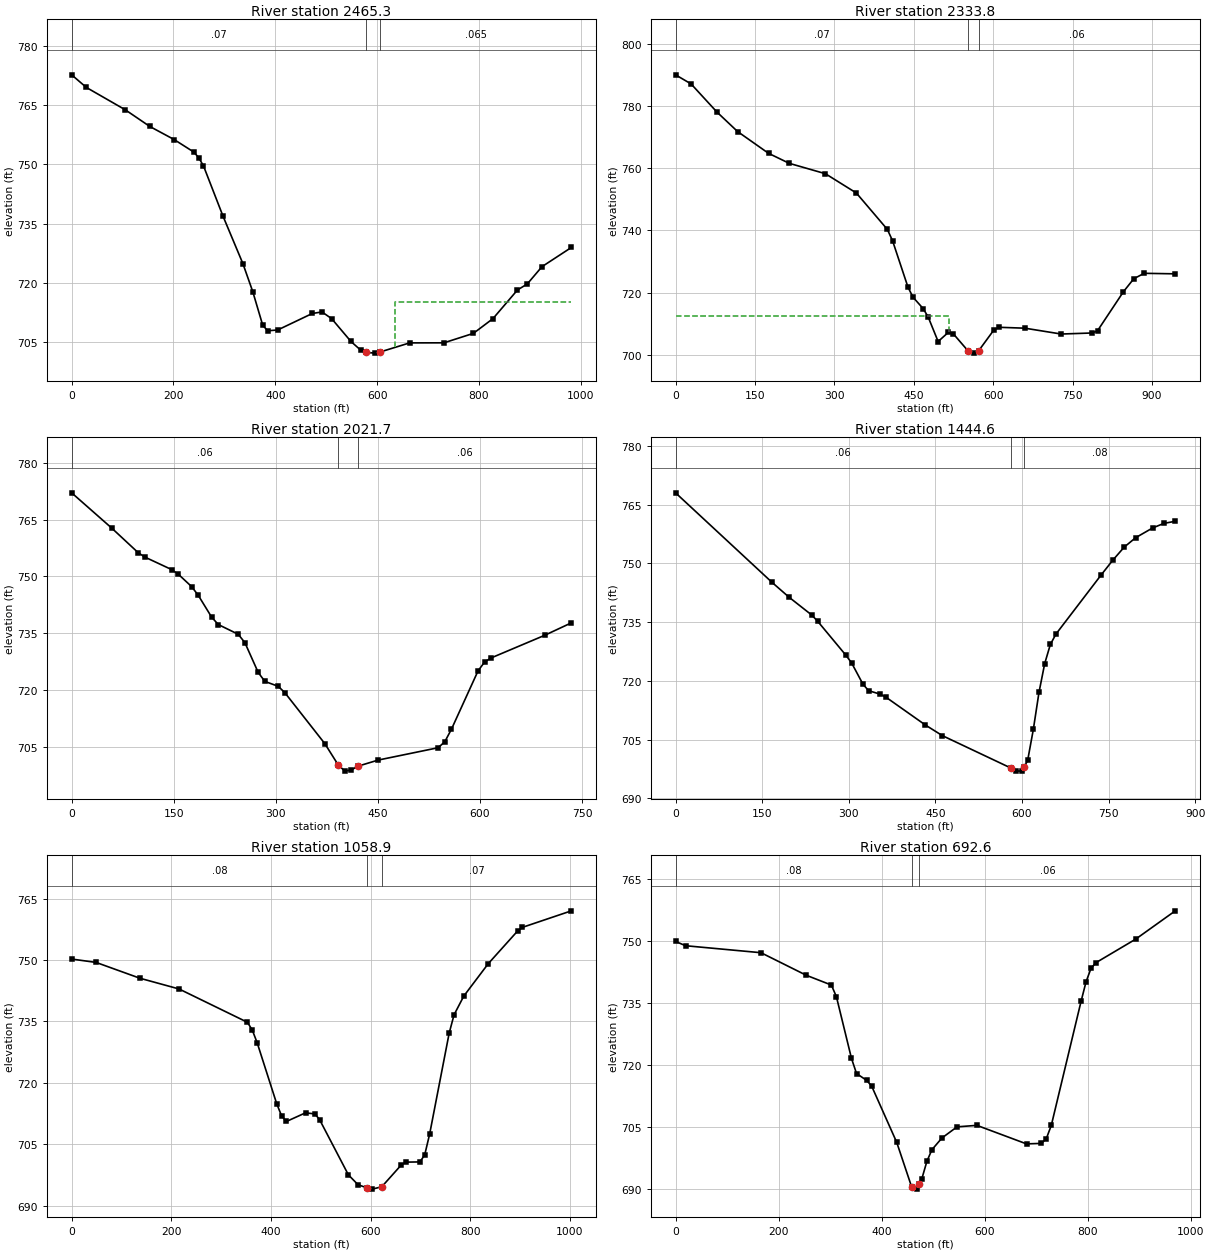
Type RM Length L Ch R = 1 ,2465.3  ,131,131.4,132.7
XS GIS Cut Line= 6
     1590542.753        341957.5     1590344.138      341736.314
     1590255.402      341596.217     1590183.356      341534.555
     1590132.665      341476.692     1590106.989      341131.111
#Sta/Elev= 30
       0  772.67    28.8  769.48   105.5   763.8   153.4   759.6   201.4  756.27
   239.7  753.13   249.3  751.73   258.9  749.61   297.3  736.86   336.3  724.86
   355.8  717.72   375.3  709.23   385.1  707.86   404.6  708.06   472.6  712.24
   491.6  712.63   510.5  710.94   548.5  705.15   567.6  702.96   577.2  702.41
   594.9   702.2     606   702.5   663.7  704.79   731.1  704.81   788.9   707.2
   827.4  710.94   875.5  718.19   894.8  719.72   923.6  724.09   981.4  728.96
#Mann= 3 , 0 , 0
       0     .07       0   577.2    .045       0     606    .065       0
#XS Ineff= 2 , 0
                          635.27          715.07
Permanent Ineff=
       F       F
Bank Sta=577.2,606
XS Rating Curve= 0 ,0
Exp/Cntr=0.3,0.1

Type RM Length L Ch R = 1 ,2333.8  ,298.8,312.2,325
XS GIS Cut Line= 6
     1590636.503      341933.195      1590472.61      341714.612
     1590383.875      341574.516     1590311.828      341512.854
     1590261.138      341454.991     1590255.427      341122.026
#Sta/Elev= 30
       0  790.04    29.3  787.12    78.1  778.08   117.1  771.81   175.6   764.8
   214.7  761.58     283  758.24   341.5  752.03     400  740.32   409.8   736.7
     439  721.73   448.5  718.51   467.5  714.89     477   712.2   495.9  704.27
   514.9  707.18   524.4  706.79   553.1  701.12   562.7  700.54   572.3  701.27
   601.2  707.99   610.8  708.85   659.8  708.56   728.3  706.68   787.1  707.02
   796.9  707.73   845.9   720.3   865.4  724.46     885  726.21   943.8  726.04
#Mann= 3 , 0 , 0
       0     .07       0   553.1    .045       0   572.3     .06       0
#XS Ineff= 2 , 0
             517  712.33
Permanent Ineff=
       F       F
Bank Sta=553.1,572.3
XS Rating Curve= 0 ,0
Exp/Cntr=0.3,0.1

Type RM Length L Ch R = 1 ,2021.7  ,571.4,577.1,581.7
XS GIS Cut Line= 2
     1590659.073      341789.097     1590527.128      341066.875
#Sta/Elev= 30
       0  772.05    58.7  762.76    97.9  756.21   107.7  755.06   146.8  751.78
   156.6  750.56   176.2  747.28     186  744.97   205.6  739.22   215.4  737.25
   244.7  734.68   254.5  732.47   274.1  724.58   283.9  722.22   303.5  720.93
   313.2  719.25     372  705.77   391.6  700.16   401.4  698.52   410.9  698.85
   420.9  699.84   450.3  701.44   538.4   704.7   548.2  706.28     558   709.6
   597.1  725.02   606.9   727.4   616.7  728.46     695  734.41   734.2   737.7
#Mann= 3 , 0 , 0
       0     .06       0   391.6    .045       0   420.9     .06       0
Bank Sta=391.6,420.9
XS Rating Curve= 0 ,0
Exp/Cntr=0.3,0.1

Type RM Length L Ch R = 1 ,1444.6  ,391.1,385.7,380.2
XS GIS Cut Line= 2
     1590977.705      341740.233      1591025.13      340875.926
#Sta/Elev= 30
       0  768.05   167.2  745.15   196.7  741.36   236.1  736.79   245.9  735.27
   295.1  726.53   304.9  724.59   324.6  719.14   334.4  717.48   354.1  716.61
     364  715.86   432.8   708.7   462.3  705.98   580.4  697.74   590.2  696.96
     600  696.92   603.7  697.95   609.9  699.67   619.7  707.57   629.5  717.04
   639.4   724.4   649.2   729.3     659  731.97   737.7  747.16   757.4  750.84
   777.1  754.17   796.8  756.57   826.3  759.07   845.9  760.24   865.6  760.78
#Mann= 3 , 0 , 0
       0     .06       0   580.4    .045       0   603.7     .08       0
Bank Sta=580.4,603.7
XS Rating Curve= 0 ,0
Exp/Cntr=0.3,0.1

Type RM Length L Ch R = 1 ,1058.9  ,361.1,366.3,370.8
XS GIS Cut Line= 4
     1591569.026      341742.615     1591426.707      341335.733
     1591375.144      341063.115     1591258.262      340792.962
#Sta/Elev= 30
       0  750.23      49  749.41   137.2  745.54   215.5  742.93   352.7   734.8
   362.5   732.9   372.3   729.8   411.5  714.92   421.3  711.97     431  710.59
   469.3   712.7   488.5  712.43     498  710.94   555.4  697.56   574.6  695.17
   593.7  694.34   603.3  694.08   622.4  694.66   660.7  699.87   670.2  700.67
   698.9  700.72   708.5  702.43   718.3  707.44   757.6  732.14   767.4  736.62
     787   741.2   836.1  749.11   894.9  757.07   904.7  757.97  1002.9     762
#Mann= 3 , 0 , 0
       0     .08       0   593.7    .045       0   622.4     .07       0
Bank Sta=593.7,622.4
XS Rating Curve= 0 ,0
Exp/Cntr=0.3,0.1

Type RM Length L Ch R = 1 ,692.6   ,698.8,692.6,685.9
XS GIS Cut Line= 3
     1591720.067      341569.004     1591730.484      341032.546
     1591595.067      340621.087
#Sta/Elev= 30
       0  749.97    19.5  748.93   165.8  747.24   253.6  741.79   302.4  739.42
   312.2  736.57   341.4  721.67   351.2  718.02   370.7  716.38   380.5  714.99
   429.2  701.37   458.3  690.54   468.3  690.07   473.3  691.38     478  692.61
   487.8  696.83   497.5  699.61     517  702.45   546.2  705.13   584.7  705.49
     681  701.01   709.8  701.13   719.4  702.27   729.1  705.48   786.8  735.45
   796.5  740.19   806.1  743.44   815.7  744.83   892.7  750.51   969.7  757.37
#Mann= 3 , 0 , 0
       0     .08       0   458.3    .045       0   473.3     .06       0
Bank Sta=458.3,473.3
XS Rating Curve= 0 ,0
Exp/Cntr=0.3,0.1

Chan Stop Cuts=-1
Use User Specified Reach Order=0
Composite Channel Slope=5